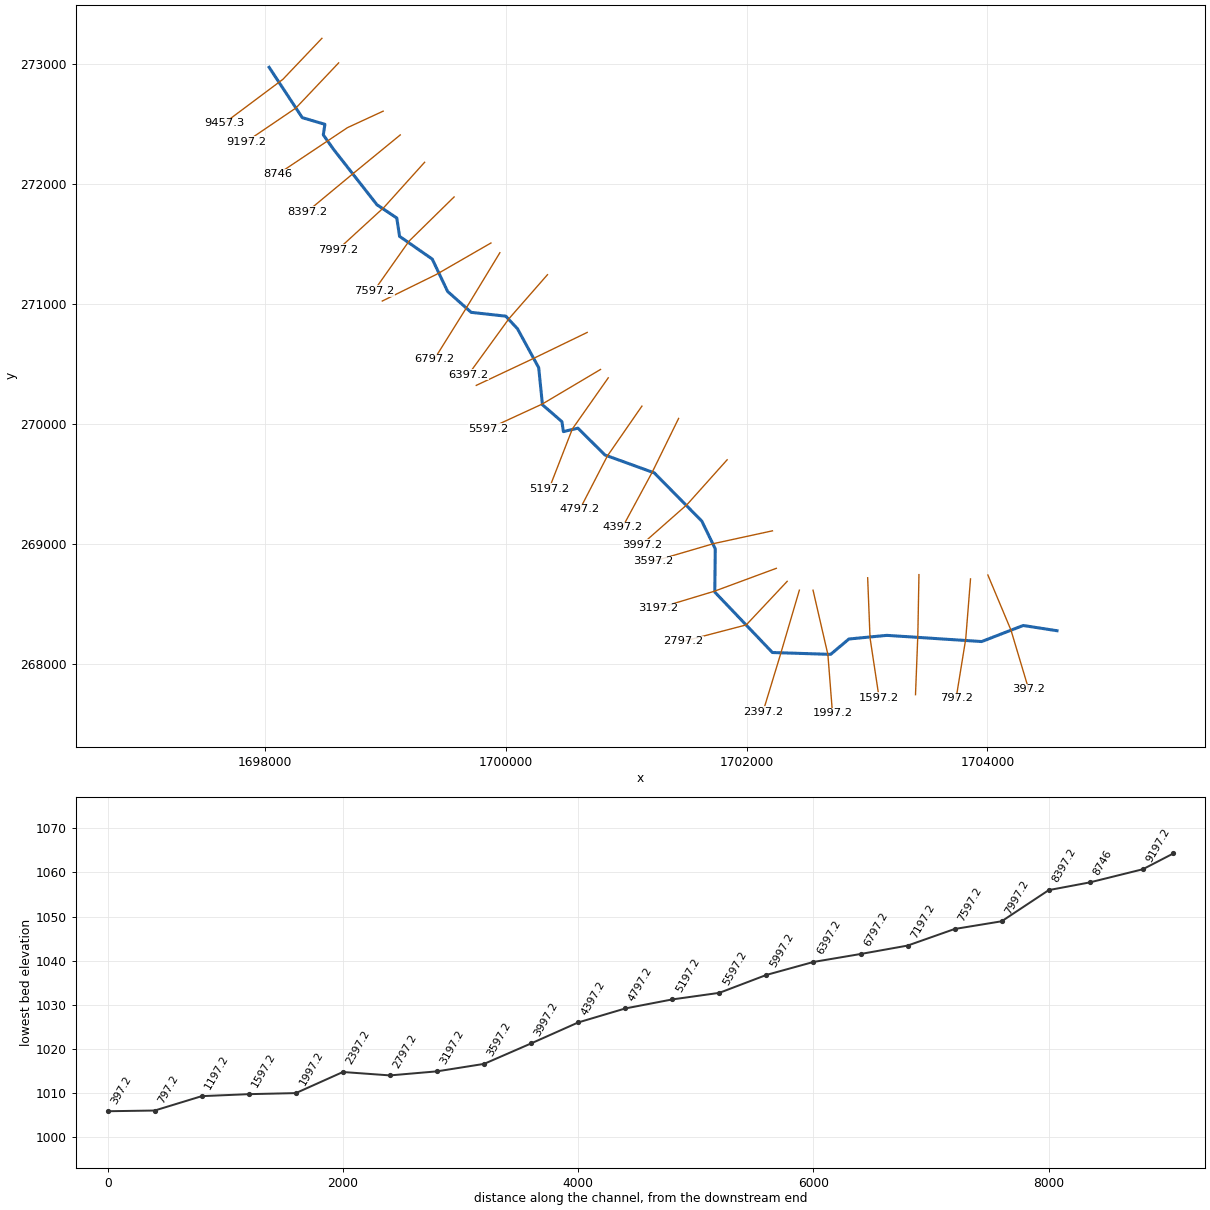
--- SycmrCrTr.prj (project) ---

Proj Title=SycmrCrTr
Current Plan=p01
Geom File=g01
Flow File=f01
Plan File=p01
DSS Export Rating Curves=0
DSS Export Rating Curve Sorted=0
DSS Export Volume Flow Curves=0
DXF OffsetX=0
DXF OffsetY=0
DXF ScaleX=0
DXF ScaleY=0

--- SycmrCrTr.p01 (plan) ---

Plan Title=Floodplain
Program Version=4.00
Geom File=g01
Flow File=f01
K Sum by GR=0
Std Step Tol=0.01
Critical Tol=0.01
Num of Std Step Trials=20
Max Error Tol=0.3
Flow Tol Ratio=0.001
Split Flow NTrial=30
Split Flow Tol=0.02
Split Flow Ratio=0.02
Log Output Level=0
Friction Slope Method=1
Unsteady Friction Slope Method=2
Unsteady Bridges Friction Slope Method=1
Global Log Level=0
CheckData=False
Run HTab=0
Run UNet=0
Run PostProcess=0
UNET Theta=0
UNET Theta Warmup=0
UNET ZTol=0
UNET ZSATol=0
UNET MxIter=0
UNET MaxInSteps=0
UNET DtIC=0
UNET DtMin=0
UNET MaxCRTS=0
UNET WFStab=0
UNET SFStab=0
UNET WFX=0
UNET SFX=0
UNET DSS MLevel=0
UNET DZMax Abort=0
UNET Convert EG Bridges=0
UNET Use Existing IB Tables=0
UNET Froude Limit=0
UNET Froude Power=0
Write IC File=0
Echo Input=False
Echo Output=False
Write Detailed=0

--- SycmrCrTr.f01 (steady flow) ---

Flow Title=NFF Regression Equation
Program Version=4.00
Number of Profiles=1
Profile Names=P100yr
River Rch & RM=SycmrCrTr,Main      ,9457.3
832.1404
River Rch & RM=SycmrCrTr,Main      ,8397.2
881.7333
River Rch & RM=SycmrCrTr,Main      ,5197.2
979.1084
River Rch & RM=SycmrCrTr,Main      ,2797.2
1080.066
River Rch & RM=SycmrCrTr,Main      ,2397.2
1605.573
River Rch & RM=SycmrCrTr,Main      ,397.2
1657.164
Boundary for River Rch & Prof#=SycmrCrTr,Main      ,1
Up Type=0
Dn Type=3
Dn Slope=0.004585

--- SycmrCrTr.g01 (geometry) ---

Geom Title=USGS 3m DEM
Program Version=4.00

River Reach=SycmrCrTr     ,Main
Reach XY= 30
     1698031.826      272974.761     1698307.023      272555.335
     1698495.147      272499.617     1698481.814      272411.635
     1698564.584      272294.203     1698927.930      271828.917
     1699092.486      271718.697     1699115.612      271565.894
     1699387.269      271376.164     1699514.649      271106.750
     1699710.296      270932.157     1699998.207      270900.269
     1700095.500      270795.301     1700271.852      270470.755
     1700302.844      270162.027     1700464.793      270021.139
     1700477.058      269937.998     1700597.881      269966.577
     1700821.835      269743.273     1701232.278      269593.917
     1701627.307      269191.577     1701739.044      268960.892
     1701735.037      268600.292     1702213.884      268096.395
     1702697.692      268080.993     1702849.572      268209.110
     1703165.335      268239.512     1703952.618      268187.908
     1704297.847      268321.767     1704578.332      268278.149

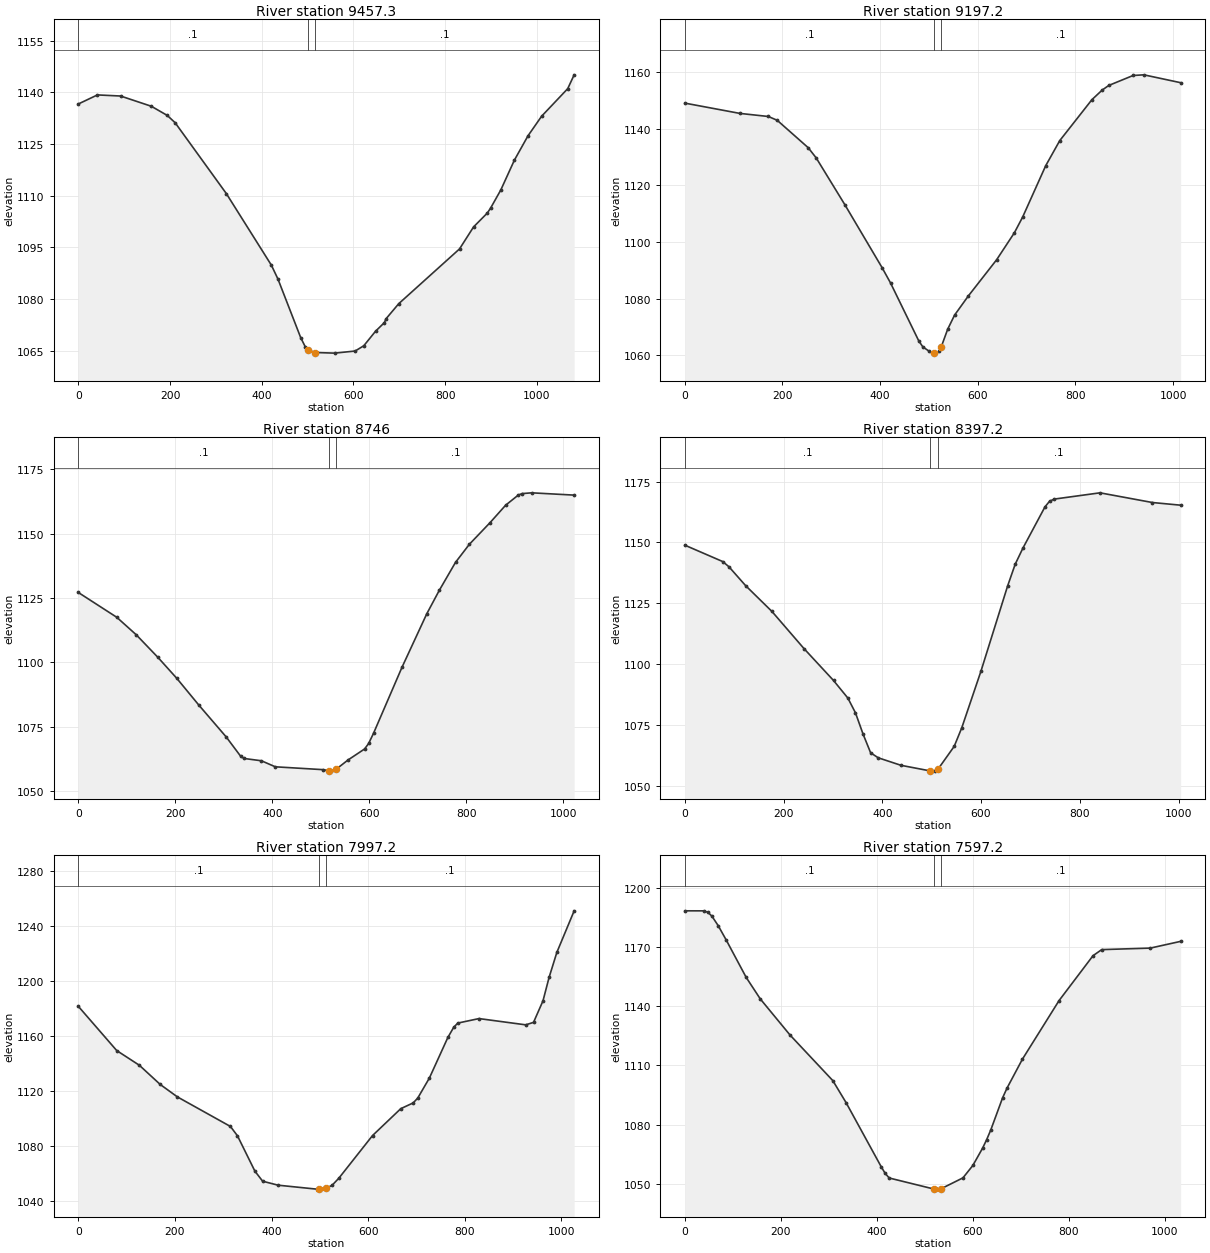
Type RM Length L Ch R = 1 ,9457.3,256.032,260.086,259.148
XS GIS Cut Line= 3
     1698470.172      273216.437     1698145.713      272874.333
     1697657.780      272508.383
#Sta/Elev= 30
       0 1136.62    41.7 1139.25    92.1 1138.93   159.2 1135.96   193.8 1133.31
   211.1 1131.19   322.8 1110.62   421.0 1089.85   435.4 1085.81   484.9 1068.85
   495.4 1066.03   501.1 1065.10   516.1 1064.50   559.2 1064.32   603.7 1064.93
   622.6 1066.46   648.2 1070.67   667.6 1073.19   670.9 1074.26   698.9 1078.68
   831.4 1094.56   862.1 1100.96   891.8 1104.94   899.1 1106.39   921.5 1111.69
   951.1 1120.34   980.8 1127.40  1010.5 1133.08  1067.4 1141.07  1081.4 1145.08
#Mann= 3 , 0 , 0
       0     0.1       0   501.1   0.045       0   516.1     0.1       0
Bank Sta=   501.1,   516.1
Exp/Cntr=0.3,0.1

Type RM Length L Ch R = 1 ,9197.2,457.291,451.214,449.275
XS GIS Cut Line= 3
     1698609.279      273011.603     1698253.903      272635.391
     1697842.280      272355.191
#Sta/Elev= 30
       0 1149.13   112.8 1145.49   171.1 1144.40   189.3 1143.05   252.7 1133.37
   269.1 1129.76   327.7 1113.24   404.0 1090.97   421.3 1085.56   479.1 1065.09
   487.5 1062.95   501.1 1061.32     510 1060.84   512.7 1060.73   521.1 1061.31
     525 1062.83   538.4 1069.18   552.5 1074.16   580.6 1080.92   638.6 1093.73
   675.0 1103.28   692.0 1108.86   739.2 1127.00   767.9 1135.86   833.8 1150.34
   854.9 1153.75   868.4 1155.38   918.2 1158.90   940.2 1159.13  1015.5 1156.35
#Mann= 3 , 0 , 0
       0     0.1       0     510   0.045       0     525     0.1       0
Bank Sta=     510,     525
Exp/Cntr=0.3,0.1

Type RM Length L Ch R = 1 ,8746,346.575,348.786,351.138
XS GIS Cut Line= 3
     1698979.306      272609.472     1698682.440      272471.788
     1698104.891      272084.694
#Sta/Elev= 30
       0 1127.17    79.3 1117.53   119.3 1110.76   164.1 1101.96   203.3 1093.76
   248.6 1083.39   305.0 1071.02   334.8 1063.52   342.1 1062.66   377.6 1061.77
   406.2 1059.43   504.7 1058.32   517.3 1057.90   521.8 1057.75   532.3 1058.57
   556.0 1062.06   590.3 1066.36   598.8 1068.52   609.0 1072.56   667.3 1098.04
   718.6 1118.90   744.3 1127.98   777.8 1138.87   806.4 1145.90   849.3 1154.36
   881.2 1161.09   907.5 1165.06   915.5 1165.61   935.1 1165.90  1022.5 1165.01
#Mann= 3 , 0 , 0
       0     0.1       0   517.3   0.045       0   532.3     0.1       0
Bank Sta=   517.3,   532.3
Exp/Cntr=0.3,0.1

Type RM Length L Ch R = 1 ,8397.2,397.737,400,399.118
XS GIS Cut Line= 3
     1699121.337      272411.214     1698731.536      272090.875
     1698347.401      271771.144
#Sta/Elev= 30
       0 1148.89    76.9 1142.14    89.4 1140.01   123.2 1132.25   176.6 1121.62
   241.3 1106.40   301.2 1093.27   330.3 1086.03   345.7 1079.96   361.0 1071.27
   376.4 1063.54   391.8 1061.48   437.9 1058.39     497 1056.09   499.3 1056.00
   506.9 1056.20     512 1056.94   514.8 1057.35   545.7 1066.19   561.1 1073.86
   599.7 1096.98   653.8 1132.07   669.2 1141.04   684.7 1147.61   729.6 1164.65
   738.8 1166.93   748.2 1167.82   841.0 1170.40   947.3 1166.41  1004.3 1165.32
#Mann= 3 , 0 , 0
       0     0.1       0     497   0.045       0     512     0.1       0
Bank Sta=     497,     512
Exp/Cntr=0.3,0.1

Type RM Length L Ch R = 1 ,7997.2,402.798,400,405.347
XS GIS Cut Line= 3
     1699323.742      272183.332     1698986.380      271807.553
     1698602.370      271454.730
#Sta/Elev= 30
       0 1181.56    79.5 1149.47   126.3 1138.82   169.6 1124.86   205.1 1115.85
   314.9 1094.41   329.5 1087.60   365.6 1061.96   381.6 1054.68   413.5 1051.80
   493.3 1048.94   497.5 1048.96   512.5 1049.55   525.1 1051.63   539.3 1056.85
   609.1 1087.82   667.6 1107.33   693.2 1111.49   702.7 1115.01   726.8 1129.56
   765.0 1158.96   777.2 1166.39   785.6 1169.41   829.5 1172.68   926.2 1168.14
   942.4 1169.93   962.0 1185.59   974.6 1202.56   990.7 1220.73  1026.5 1250.86
#Mann= 3 , 0 , 0
       0     0.1       0   497.5   0.045       0   512.5     0.1       0
Bank Sta=   497.5,   512.5
Exp/Cntr=0.3,0.1

Type RM Length L Ch R = 1 ,7597.2,400.527,400,390.276
XS GIS Cut Line= 3
     1699568.606      271894.208     1699193.668      271525.146
     1698902.191      271110.412
#Sta/Elev= 30
       0 1188.52    39.7 1188.51    48.1 1187.78    56.5 1185.80    69.4 1181.06
    86.1 1173.79   128.0 1154.67   157.2 1143.81   219.3 1125.43   308.4 1102.29
   336.0 1091.12   409.1 1058.60   417.5 1055.17   425.9 1052.84   518.6 1047.26
   526.1 1047.19   533.6 1047.34   579.5 1052.91   600.1 1059.20   620.4 1067.99
   628.9 1072.32   637.4 1077.18   662.1 1093.56   671.5 1098.58   703.4 1113.19
   779.7 1142.93   850.5 1165.74   868.6 1168.82   969.8 1169.59  1033.0 1173.01
#Mann= 3 , 0 , 0
       0     0.1       0   518.6   0.045       0   533.6     0.1       0
Bank Sta=   518.6,   533.6
Exp/Cntr=0.3,0.1

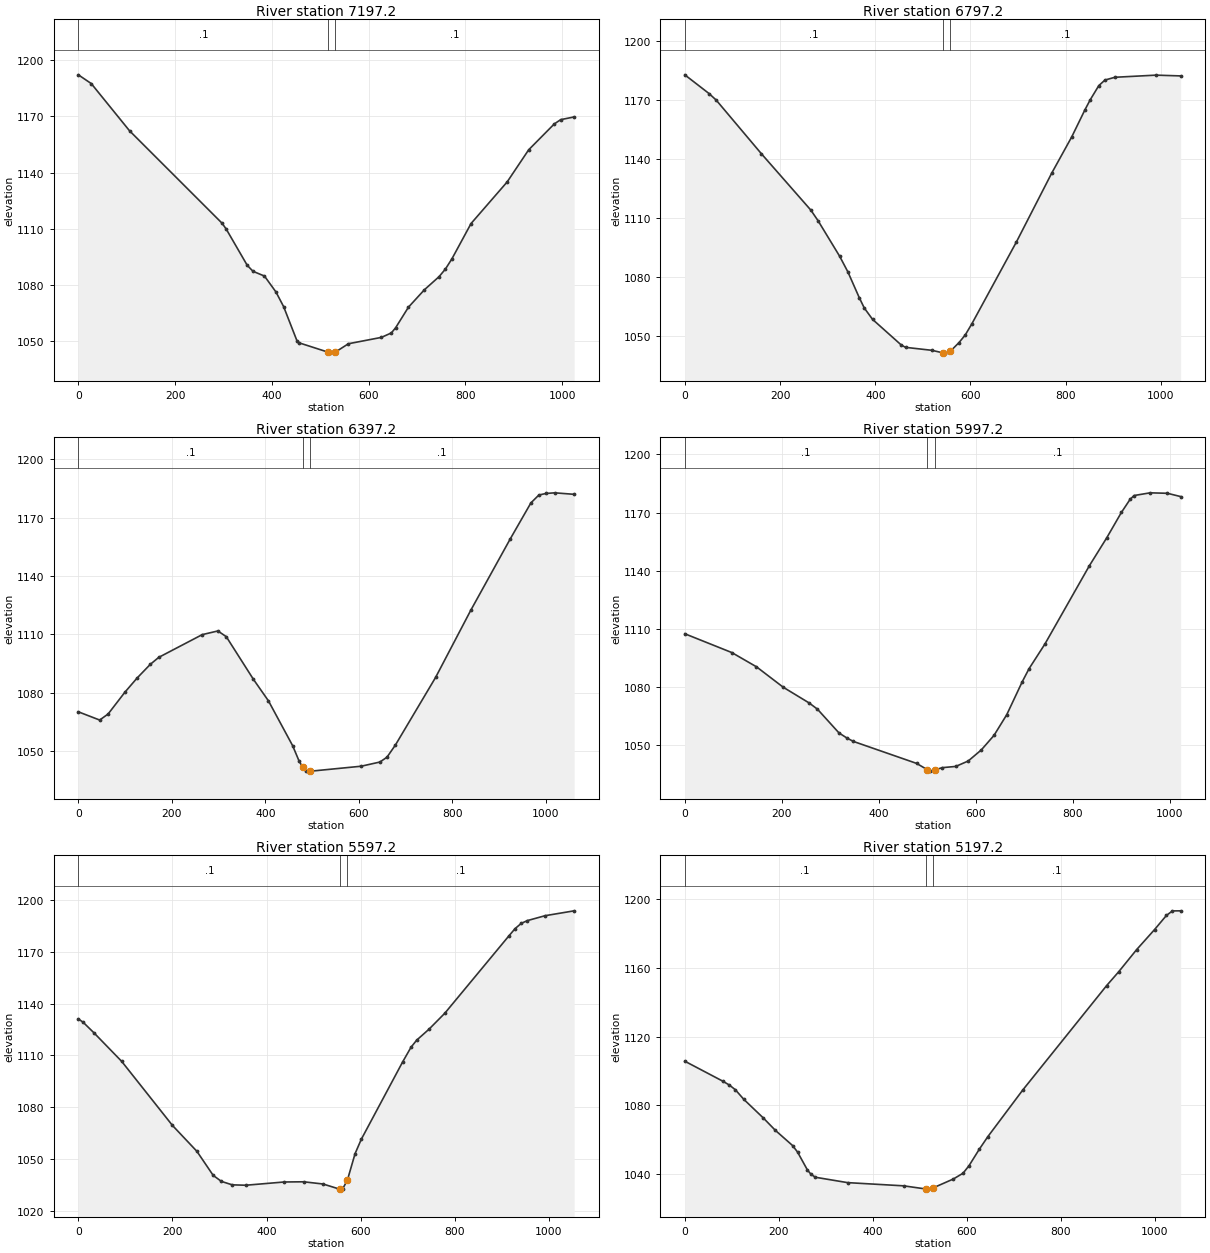
Type RM Length L Ch R = 1 ,7197.2,390.933,400,410.884
XS GIS Cut Line= 3
     1699874.714      271510.240     1699421.128      271247.963
     1698971.875      271026.432
#Sta/Elev= 30
       0 1192.26    26.7 1187.59   105.8 1162.35   296.9 1112.96   305.6 1109.81
   349.1 1090.40   361.1 1087.19   384.8 1084.63   408.5 1076.13   424.4 1068.27
   451.9 1050.04   455.9 1048.97   516.5 1043.93   520.4 1043.43   531.5 1044.02
   558.3 1048.45   626.5 1051.85   647.0 1054.23   655.8 1056.97   682.4 1068.01
   715.4 1077.33   745.6 1084.31   758.8 1088.40   772.1 1093.80   811.8 1112.75
   886.4 1134.98   930.9 1152.17   983.9 1166.02   997.1 1168.29  1024.9 1169.74
#Mann= 3 , 0 , 0
       0     0.1       0   516.5   0.045       0   531.5     0.1       0
Bank Sta=   516.5,   531.5
Exp/Cntr=0.3,0.1

Type RM Length L Ch R = 1 ,6797.2,403.436,400,404.035
XS GIS Cut Line= 3
     1699949.130      271429.233     1699663.975      270958.650
     1699404.358      270541.151
#Sta/Elev= 30
       0 1182.73    50.8 1173.25    65.8 1169.95   160.9 1142.68   264.7 1114.09
   279.9 1108.69   325.2 1090.68   342.5 1082.74   366.5 1069.61   377.0 1064.39
   394.4 1058.63   454.8 1045.60   463.7 1044.45   519.2 1042.94   542.7 1041.62
   547.0 1041.52   557.7 1042.47   575.8 1046.85   588.9 1050.70   602.9 1056.41
   696.5 1097.96   770.6 1132.86   812.6 1151.23   840.5 1165.05   851.6 1170.13
   869.5 1177.27   882.5 1180.10   903.4 1181.49   989.6 1182.57  1041.3 1182.18
#Mann= 3 , 0 , 0
       0     0.1       0   542.7   0.045       0   557.7     0.1       0
Bank Sta=   542.7,   557.7
Exp/Cntr=0.3,0.1

Type RM Length L Ch R = 1 ,6397.2,409.133,400,388.554
XS GIS Cut Line= 3
     1700344.637      271246.138     1700024.107      270878.646
     1699688.075      270414.037
#Sta/Elev= 30
       0 1070.22    45.7 1065.98    63.7 1069.09    99.9 1080.37   125.7 1087.57
   154.1 1094.64   172.1 1098.22   265.1 1109.90   298.6 1111.79   316.6 1108.84
   374.5 1086.98   406.9 1075.82   458.7 1052.75   472.3 1044.94   480.1 1041.72
   487.6 1039.96   495.1 1039.79   498.4 1039.72   605.2 1042.24   645.4 1044.40
   660.5 1046.90   678.5 1053.14   764.5 1087.90   839.7 1122.39   923.8 1158.93
   968.5 1177.65   985.5 1181.68  1000.9 1182.49  1019.5 1182.81  1061.0 1182.04
#Mann= 3 , 0 , 0
       0     0.1       0   480.1   0.045       0   495.1     0.1       0
Bank Sta=   480.1,   495.1
Exp/Cntr=0.3,0.1

Type RM Length L Ch R = 1 ,5997.2,398.186,400,399.717
XS GIS Cut Line= 3
     1700674.869      270764.814     1700218.148      270542.948
     1699752.916      270323.321
#Sta/Elev= 30
       0 1107.59    96.9 1097.90   147.8 1090.55   202.9 1080.03   256.4 1071.91
   273.5 1068.71   317.9 1056.46   334.5 1053.80   347.7 1052.08   477.8 1040.77
   500.3 1037.49   506.1 1036.78   515.3 1037.42   531.2 1038.58   558.6 1039.20
   584.3 1042.00   611.2 1047.69   637.4 1055.18   663.7 1065.85   695.5 1082.76
   709.6 1089.54   742.4 1102.29   834.1 1142.66   870.1 1157.13   900.0 1170.09
   918.0 1176.86   926.3 1178.84   959.3 1180.23   995.0 1179.99  1022.2 1178.30
#Mann= 3 , 0 , 0
       0     0.1       0   500.3   0.045       0   515.3     0.1       0
Bank Sta=   500.3,   515.3
Exp/Cntr=0.3,0.1

Type RM Length L Ch R = 1 ,5597.2,396.932,400,411.895
XS GIS Cut Line= 3
     1700785.512      270456.065     1700300.543      270167.353
     1699856.533      269962.097
#Sta/Elev= 30
       0 1131.11    10.1 1129.21    33.3 1123.05    92.1 1106.58   200.0 1069.54
   252.0 1054.56   286.6 1040.66   304.0 1037.19   327.0 1035.20   355.9 1034.97
   437.5 1036.85   478.9 1036.96   520.0 1035.68   555.1 1032.72   556.9 1032.76
   561.8 1032.89   571.9 1038.07   588.1 1053.26   601.2 1061.49   689.0 1106.19
   706.9 1114.72   718.9 1118.82   745.1 1125.15   778.5 1134.33   915.1 1179.17
   928.2 1183.35   941.3 1186.37   954.4 1187.97   992.1 1190.80  1053.6 1193.60
#Mann= 3 , 0 , 0
       0     0.1       0   556.9   0.045       0   571.9     0.1       0
Bank Sta=   556.9,   571.9
Exp/Cntr=0.3,0.1

Type RM Length L Ch R = 1 ,5197.2,392.152,400,402.246
XS GIS Cut Line= 3
     1700849.785      270386.275     1700551.615      269960.395
     1700357.799      269461.109
#Sta/Elev= 30
       0 1105.77    80.5 1094.19    95.0 1091.84   107.7 1089.12   125.8 1083.49
   167.2 1072.67   192.9 1065.45   229.3 1056.65   239.9 1052.87   261.1 1042.35
   268.9 1039.79   278.2 1038.14   346.4 1035.02   465.7 1033.15   512.4 1031.34
   515.3 1031.23   527.4 1031.81   571.7 1037.14   592.3 1040.51   605.0 1044.89
   626.7 1054.41   645.1 1061.83   719.6 1089.06   897.9 1149.82   923.4 1157.82
   961.6 1170.73   999.8 1182.43  1025.3 1190.74  1038.0 1193.34  1055.4 1193.39
#Mann= 3 , 0 , 0
       0     0.1       0   512.4   0.045       0   527.4     0.1       0
Bank Sta=   512.4,   527.4
Exp/Cntr=0.3,0.1

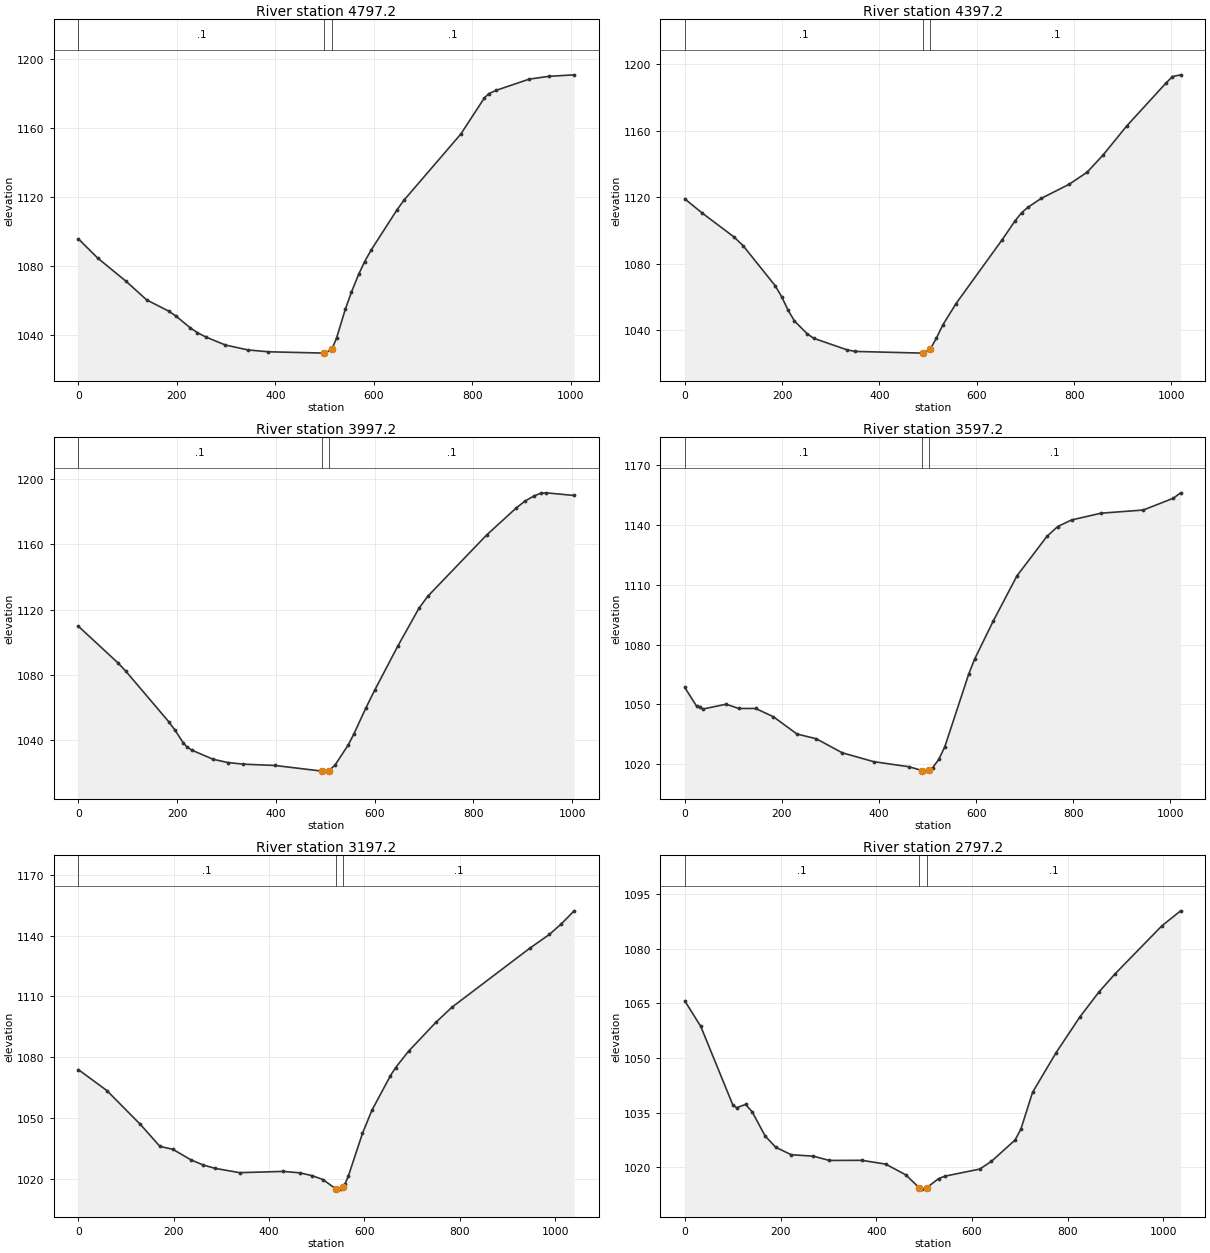
Type RM Length L Ch R = 1 ,4797.2,396.637,400,399.581
XS GIS Cut Line= 3
     1701129.496      270150.664     1700841.508      269733.150
     1700613.042      269289.167
#Sta/Elev= 30
       0 1095.67    39.1 1084.50    96.8 1070.98   138.7 1060.14   183.3 1053.62
   197.7 1050.83   226.6 1044.04   241.9 1041.05   259.0 1038.54   298.7 1033.88
   344.4 1031.04   385.2 1029.97   499.7 1029.19   500.6 1029.18   514.7 1031.45
   524.2 1037.98   541.8 1054.56   554.5 1064.75   568.9 1074.91   581.2 1082.39
   594.6 1089.21   646.8 1112.46   661.3 1118.20   776.5 1156.59   823.9 1177.42
   832.7 1179.96   848.3 1181.98   915.0 1188.47   955.1 1190.12  1006.5 1190.99
#Mann= 3 , 0 , 0
       0     0.1       0   499.7   0.045       0   514.7     0.1       0
Bank Sta=   499.7,   514.7
Exp/Cntr=0.3,0.1

Type RM Length L Ch R = 1 ,4397.2,406.192,400,392.009
XS GIS Cut Line= 3
     1701434.379      270047.991     1701216.130      269601.816
     1700968.724      269142.094
#Sta/Elev= 30
       0 1118.95    35.5 1110.47   101.0 1096.04   119.8 1090.76   185.9 1066.56
   199.1 1059.96   212.3 1051.86   225.2 1045.43   251.7 1037.60   265.2 1034.92
   332.7 1028.07   349.5 1027.04   489.2 1026.02   489.8 1026.01   504.2 1028.34
   516.7 1034.90   530.2 1043.02   557.1 1055.78   651.5 1094.08   678.5 1105.65
   692.0 1110.62   705.4 1113.96   732.4 1119.25   789.6 1127.73   826.8 1135.03
   859.7 1145.46   907.7 1162.77   988.6 1188.71  1002.1 1192.65  1018.8 1193.70
#Mann= 3 , 0 , 0
       0     0.1       0   489.2   0.045       0   504.2     0.1       0
Bank Sta=   489.2,   504.2
Exp/Cntr=0.3,0.1

Type RM Length L Ch R = 1 ,3997.2,414.212,400,390.075
XS GIS Cut Line= 3
     1701837.719      269703.187     1701504.985      269330.108
     1701127.417      268996.149
#Sta/Elev= 30
       0 1109.82    79.9 1087.51    95.8 1082.47   183.5 1051.31   196.0 1046.16
   212.8 1038.43   219.2 1036.30   229.6 1034.13   272.7 1028.52   302.6 1026.52
   334.4 1025.51   397.5 1024.74   492.4 1021.30   493.5 1021.26   507.4 1021.57
   519.9 1025.00   546.4 1037.22   557.6 1043.72   582.3 1059.89   600.2 1070.79
   646.7 1097.56   689.8 1120.83   707.7 1128.16   826.7 1165.54   886.9 1182.12
   904.8 1186.36   922.8 1189.46   936.1 1191.03   947.9 1191.33  1004.0 1189.70
#Mann= 3 , 0 , 0
       0     0.1       0   492.4   0.045       0   507.4     0.1       0
Bank Sta=   492.4,   507.4
Exp/Cntr=0.3,0.1

Type RM Length L Ch R = 1 ,3597.2,396.79,400,400.219
XS GIS Cut Line= 3
     1702214.245      269110.882     1701729.378      269005.263
     1701226.052      268857.180
#Sta/Elev= 30
       0 1058.49    24.3 1049.13    31.3 1048.93    36.5 1047.66    85.1 1050.12
   111.1 1047.98   145.8 1047.99   182.3 1043.87   230.9 1035.20   270.7 1032.82
   324.2 1025.80   388.8 1021.36   461.7 1018.81   488.7 1016.91   498.2 1016.62
   503.7 1017.38   510.6 1018.43   523.0 1022.49   535.4 1028.86   584.9 1065.44
   597.2 1072.95   635.2 1091.80   683.9 1114.37   745.8 1134.18   767.8 1139.06
   796.5 1142.36   857.1 1145.74   943.8 1147.31  1005.6 1153.19  1020.9 1155.93
#Mann= 3 , 0 , 0
       0     0.1       0   488.7   0.045       0   503.7     0.1       0
Bank Sta=   488.7,   503.7
Exp/Cntr=0.3,0.1

Type RM Length L Ch R = 1 ,3197.2,389.651,400,392.891
XS GIS Cut Line= 3
     1702246.437      268798.400     1701733.040      268607.846
     1701262.128      268464.997
#Sta/Elev= 30
       0 1073.89    59.7 1063.57   130.1 1046.85   171.1 1036.01   198.3 1034.56
   235.7 1029.42   262.3 1026.79   287.6 1025.14   338.3 1023.05   429.7 1023.67
   464.9 1022.95   490.3 1021.57   512.8 1019.67   540.1 1015.05   540.9 1014.93
   549.8 1015.01   555.1 1016.16   559.4 1017.58   565.9 1021.17   595.8 1042.42
   615.5 1053.77   654.5 1070.89   665.1 1074.82   692.6 1082.98   749.7 1097.17
   783.3 1104.62   946.9 1133.79   987.7 1140.53  1012.5 1145.69  1039.7 1152.19
#Mann= 3 , 0 , 0
       0     0.1       0   540.1   0.045       0   555.1     0.1       0
Bank Sta=   540.1,   555.1
Exp/Cntr=0.3,0.1

Type RM Length L Ch R = 1 ,2797.2,389.101,400,429.524
XS GIS Cut Line= 3
     1702336.656      268689.728     1701996.519      268326.568
     1701475.856      268190.177
#Sta/Elev= 30
       0 1065.65    33.4 1058.63   100.5 1037.06   108.3 1036.34   127.0 1037.25
   140.9 1035.19   167.7 1028.61   189.7 1025.52   222.2 1023.45   268.5 1023.05
   302.1 1021.88   370.1 1021.91   419.7 1020.87   461.7 1017.92   490.1 1014.34
   495.3 1014.01   505.1 1014.36   530.2 1016.90   543.6 1017.57   616.2 1019.51
   640.7 1021.65   689.8 1027.46   702.1 1030.47   726.6 1040.60   775.7 1051.45
   824.8 1061.14   864.6 1068.00   898.4 1073.00   996.6 1086.23  1035.8 1090.35
#Mann= 3 , 0 , 0
       0     0.1       0   490.1   0.045       0   505.1     0.1       0
Bank Sta=   490.1,   505.1
Exp/Cntr=0.3,0.1

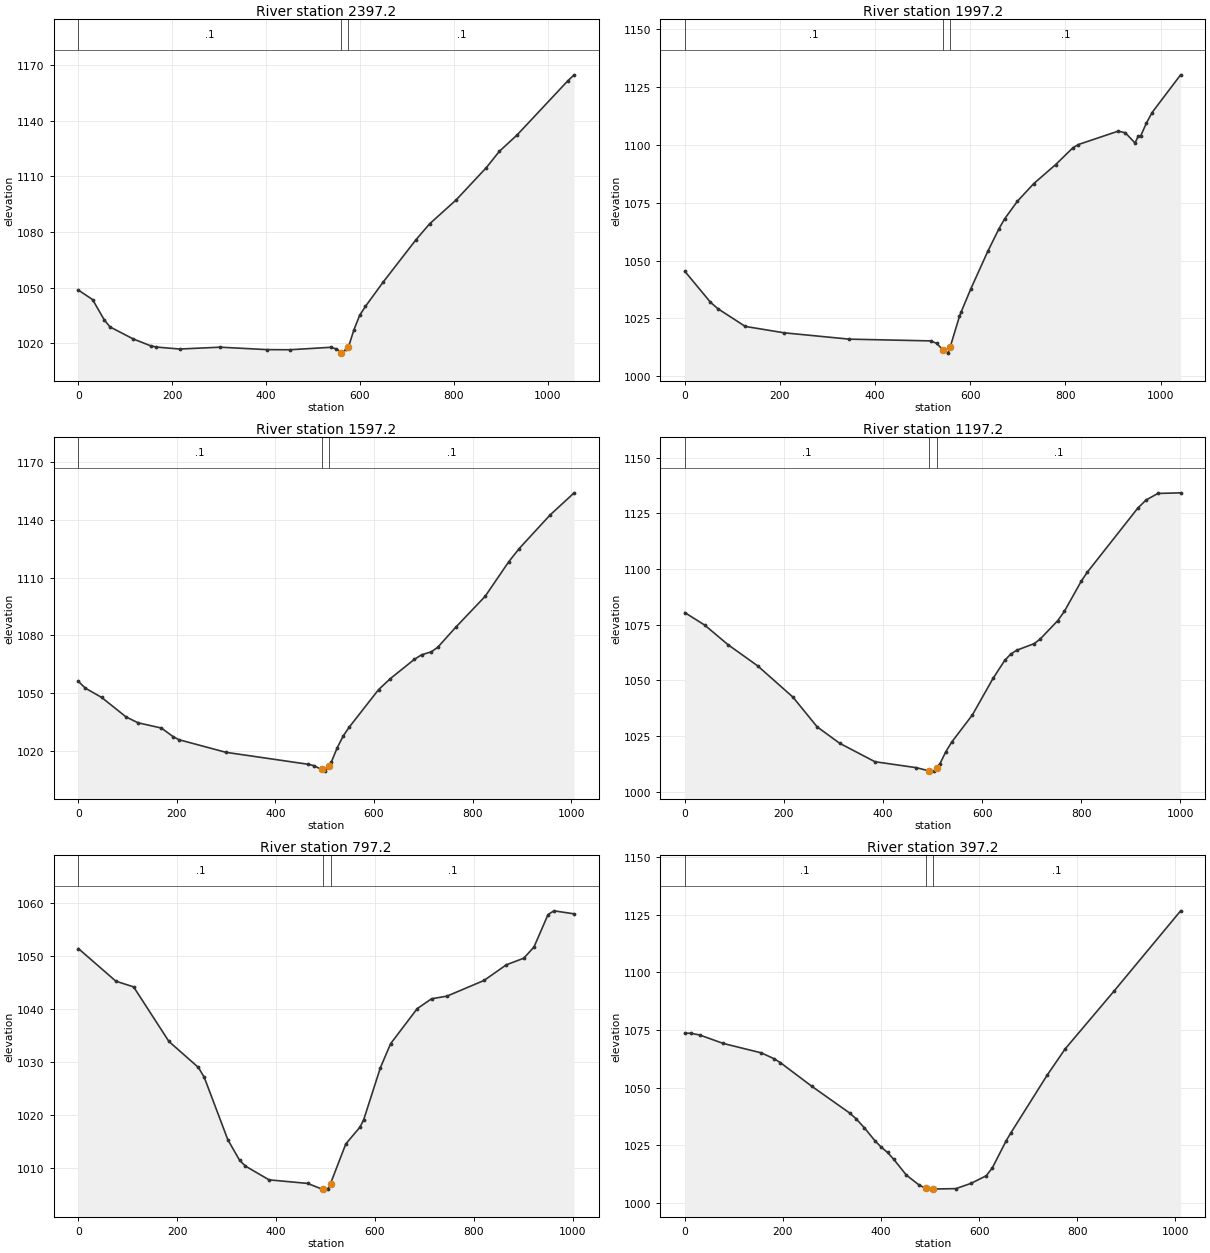
Type RM Length L Ch R = 1 ,2397.2,388.451,400,408.402
XS GIS Cut Line= 3
     1702437.818      268616.095     1702277.929      268070.881
     1702136.119      267603.399
#Sta/Elev= 30
       0 1048.76    30.4 1043.62    55.2 1032.71    67.5 1028.90   117.0 1022.42
   154.1 1018.73   166.5 1018.04   216.0 1016.99   302.6 1017.98   401.6 1016.67
   451.1 1016.60   537.7 1017.92   550.1 1017.04   560.7 1015.10   562.4 1014.78
   571.2 1017.05   574.8 1017.40   575.7 1018.03   587.2 1027.23   599.6 1035.15
   612.0 1039.98   649.3 1052.93   719.5 1075.83   748.5 1084.38   805.2 1097.30
   869.4 1114.65   897.4 1123.51   934.6 1132.16  1043.2 1161.45  1056.7 1164.67
#Mann= 3 , 0 , 0
       0     0.1       0   560.7   0.045       0   575.7     0.1       0
Bank Sta=   560.7,   575.7
Exp/Cntr=0.3,0.1

Type RM Length L Ch R = 1 ,1997.2,404.115,400,401.777
XS GIS Cut Line= 3
     1702551.569      268615.745     1702674.883      268079.322
     1702713.201      267589.119
#Sta/Elev= 30
       0 1045.36    53.9 1031.99    69.5 1029.20   127.0 1021.54   208.2 1018.79
   345.5 1016.04   516.9 1015.28   529.1 1014.24   542.9 1011.37   553.4 1010.00
   557.9 1012.73   577.2 1025.84   581.0 1027.87   601.0 1037.69   636.7 1053.92
   660.5 1063.80   672.4 1068.05   699.0 1075.58   733.4 1083.21   779.6 1091.45
   815.3 1098.62   827.3 1100.09   910.6 1105.85   925.6 1105.20   946.3 1100.78
   953.0 1103.71   958.3 1103.87   970.2 1109.37   982.1 1113.91  1042.1 1130.19
#Mann= 3 , 0 , 0
       0     0.1       0   542.9   0.045       0   557.9     0.1       0
Bank Sta=   542.9,   557.9
Exp/Cntr=0.3,0.1

Type RM Length L Ch R = 1 ,1597.2,401.293,400,395.714
XS GIS Cut Line= 3
     1703005.409      268719.830     1703025.055      268219.227
     1703100.381      267719.665
#Sta/Elev= 30
       0 1056.28    14.2 1052.73    47.4 1047.92    96.9 1037.82   121.1 1034.80
   168.7 1032.06   192.4 1027.61   204.3 1026.02   299.4 1019.51   465.7 1013.34
   477.6 1012.63   493.5 1010.64   501.0 1009.76   508.5 1012.43   513.4 1014.43
   525.4 1021.89   537.4 1027.90   549.4 1032.43   609.4 1052.01   633.4 1057.71
   681.5 1067.57   696.5 1070.00   716.5 1071.57   729.5 1073.93   765.5 1084.16
   825.5 1100.26   873.6 1118.25   894.7 1125.03   957.3 1142.40  1006.2 1153.88
#Mann= 3 , 0 , 0
       0     0.1       0   493.5   0.045       0   508.5     0.1       0
Bank Sta=   493.5,   508.5
Exp/Cntr=0.3,0.1

Type RM Length L Ch R = 1 ,1197.2,401.371,400,397.267
XS GIS Cut Line= 3
     1703431.610      268745.699     1703422.370      268245.307
     1703402.969      267745.058
#Sta/Elev= 30
       0 1080.48    40.1 1074.88    87.6 1066.01   146.9 1056.60   218.2 1042.55
   267.1 1029.19   312.6 1021.81   383.7 1013.54   467.6 1010.85     493 1009.42
   503.2 1009.31     508 1010.62   515.1 1012.70   526.9 1018.07   538.8 1022.39
   580.4 1034.53   622.0 1050.91   645.8 1059.05   657.6 1061.79   669.5 1063.54
   705.2 1066.55   717.0 1068.55   752.7 1076.86   765.9 1080.98   800.2 1094.59
   812.1 1098.54   914.2 1127.36   930.9 1131.01   954.7 1133.96  1000.7 1134.24
#Mann= 3 , 0 , 0
       0     0.1       0     493   0.045       0     508     0.1       0
Bank Sta=     493,     508
Exp/Cntr=0.3,0.1

Type RM Length L Ch R = 1 ,797.2,389.242,400,410.181
XS GIS Cut Line= 3
     1703860.111      268710.191     1703820.225      268209.293
     1703740.472      267715.543
#Sta/Elev= 30
       0 1051.45    76.0 1045.28   111.8 1044.21   183.2 1033.91   242.7 1029.02
   254.7 1027.13   302.3 1015.37   326.1 1011.50   338.0 1010.39   385.7 1007.80
   463.4 1007.13   492.9 1006.05     495 1006.07   504.8 1006.12     510 1007.11
   540.9 1014.59   569.4 1017.73   577.0 1019.14   610.8 1028.97   631.5 1033.50
   685.2 1040.10   714.3 1041.97   745.3 1042.46   820.3 1045.42   865.6 1048.38
   900.7 1049.62   921.4 1051.74   949.8 1057.86   961.8 1058.56  1002.6 1057.99
#Mann= 3 , 0 , 0
       0     0.1       0     495   0.045       0     510     0.1       0
Bank Sta=     495,     510
Exp/Cntr=0.3,0.1

Type RM Length L Ch R = 1 ,397.2,412.485,397.176,384.262
XS GIS Cut Line= 3
     1704004.228      268742.683     1704196.378      268282.839
     1704342.810      267791.665
#Sta/Elev= 30
       0 1073.61    12.3 1073.54    30.4 1072.80    78.7 1069.11   156.0 1065.04
   181.7 1062.54   194.6 1060.84   258.9 1050.54   336.1 1038.93   349.0 1036.49
   366.2 1032.50   387.6 1026.91   400.4 1024.13   413.3 1021.83   426.2 1018.79
   451.9 1011.95   477.6 1007.69   490.9 1006.24   503.2 1005.89   505.9 1005.93
   552.7 1006.11   583.6 1008.40   614.7 1011.71   627.1 1015.17   655.3 1026.91
   664.2 1030.11   738.6 1055.30   775.7 1066.82   874.9 1091.80  1010.9 1126.70
#Mann= 3 , 0 , 0
       0     0.1       0   490.9   0.045       0   505.9     0.1       0
Bank Sta=   490.9,   505.9
Exp/Cntr=0.3,0.1